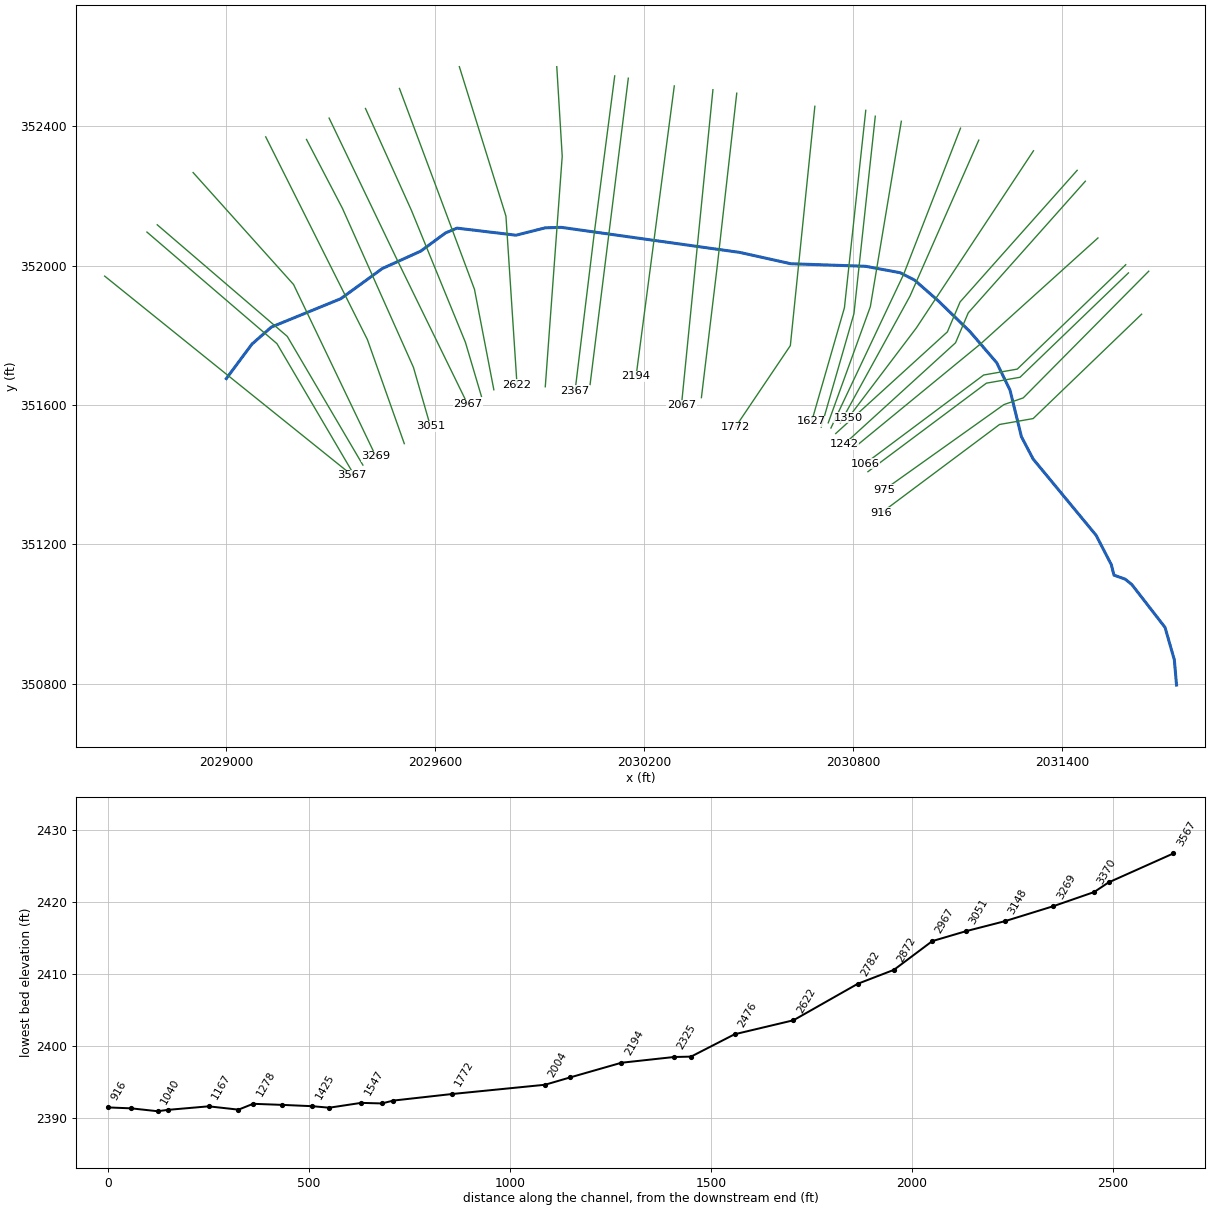
--- WOLFPENCK.prj (project) ---

Proj Title=WOLFPENCK
Current Plan=p01
Default Exp/Contr=0,0
English Units
Geom File=g01
Flow File=f01
Plan File=p01
BEGIN DESCRIPTION:
Stream Name- Wolfpen Creek
Flood Zone: Zone A
Greenbrier County, WV
County-Wide Study
WVDHSEM-2018-3, Flood Risk Project
HEC-RAS Version: 5.0.7
General Notes:
For the Hydrology Regression was used.
END DESCRIPTION:
DSS Export Rating Curves= 0
DSS Export Rating Curve Sorted= 0
DSS Export Volume Flow Curves= 0
DXF OffsetX= 0
DXF OffsetY= 0
DXF ScaleX= 0
DXF ScaleY= 0

--- WOLFPENCK.p01 (plan) ---

Plan Title=Floodplain
Program Version=5.07
Short Identifier=Floodplain
Geom File=g01
Flow File=f01
Subcritical Flow
K Sum by GR= 0
Std Step Tol= 0.01
Critical Tol= 0.01
Num of Std Step Trials= 20
Max Error Tol= 0.3
Flow Tol Ratio= 0.001
Split Flow NTrial= 30
Split Flow Tol= 0.02
Split Flow Ratio= 0.02
Log Output Level= 0
Friction Slope Method= 1
Unsteady Friction Slope Method= 2
Unsteady Bridges Friction Slope Method= 1
Parabolic Critical Depth
Global Vel Dist= 0 , 0 , 0
Global Log Level= 0
CheckData=True
Encroach Param=-1 ,0,0, 0
Mapping Interval=1HOUR
Computation Time Step Use Courant=        0
Computation Time Step Use Time Series=    0
Computation Time Step Count To Double=0
Computation Time Step Max Doubling=0
Computation Time Step Max Halving=0
Computation Time Step Residence Courant=0
Run HTab= 0
Run UNet= 0
Run Sediment= 0
Run PostProcess= 0
Run WQNet= 0
Run RASMapper= 0
UNET Theta= 0
UNET Theta Warmup= 0
UNET ZTol= 0
UNET ZSATol= 0
UNET MxIter= 0
UNET Max Iter WO Improvement= 0
UNET MaxInSteps= 0
UNET DtIC= 0
UNET DtMin= 0
UNET MaxCRTS= 0
UNET WFStab= 0
UNET SFStab= 0
UNET WFX= 1
UNET SFX= 1
UNET 1D Methodology=Finite Difference
UNET DSS MLevel= 1
UNET Pardiso=0
UNET DZMax Abort= 0
UNET Use Existing IB Tables= 0
UNET Froude Reduction=False
UNET Froude Limit= 0
UNET Froude Power= 0
UNET D1 Cores= 0
UNET D2 Coriolis=0
UNET D2 Cores= 0
UNET D2 Theta= 1
UNET D2 Theta Warmup= 1
UNET D2 Z Tol= 0.01
UNET D2 Volume Tol= 0.01
UNET D2 Max Iterations= 20
UNET D2 Equation= 0
UNET D2 RampUpFraction=0.1
UNET D2 TimeSlices= 1
UNET D2 BCVolumeCheck=0
UNET D1D2 MaxIter= 0
UNET D1D2 ZTol=0.01
UNET D1D2 QTol=0.1
UNET D1D2 MinQTol=1
Write IC File= 0
Write IC File at Fixed DateTime=0
Write IC File at Sim End=0
Echo Input=False
Echo Parameters=False
Echo Output=False
Write Detailed= 0
HDF Write Warmup=0
HDF Write Time Slices=0
HDF Flush=0
HDF Face Node Velocities=0
HDF Compression= 1
HDF Chunk Size= 1
HDF Spatial Parts= 1
HDF Use Max Rows=0
HDF Fixed Rows= 1
Calibration Method= 0
Calibration Iterations= 20
Calibration Max Change=0.05
Calibration Tolerance=0.2
Calibration Maximum=1.5
Calibration Minimum=0.5
Calibration Optimization Method= 1
WQ AD Non Conservative
WQ ULTIMATE=-1
WQ Max Comp Step=1HOUR
WQ Output Interval=15MIN
WQ Output Selected Increments= 0
WQ Output face flow=0
WQ Output face velocity=0
WQ Output face area=0
WQ Output face dispersion=0
WQ Output cell volume=0
WQ Output cell surface area=0
WQ Output cell continuity=0
WQ Output cumulative cell continuity=0
WQ Output face conc=0
WQ Output face dconc_dx=0
WQ Output face courant=0
WQ Output face peclet=0
WQ Output face adv mass=0
WQ Output face disp mass=0
WQ Output cell mass=0
WQ Output cell source sink temp=0
WQ Output nsm pathways=0
WQ Output nsm derived pathways=0
WQ Output MaxMinRange=-1
WQ Daily Max Min Mean=-1
WQ Daily Range=0
WQ Daily Time=0
WQ Create Restart=0
WQ Fixed Restart=0
WQ System Summary=0
WQ Write To DSS=0
WQ Use Fixed Temperature=0
Sorting and Armoring Iterations= 10
XS Update Threshold= 0.02
Bed Roughness Predictor= 0
Hydraulics Update Threshold= 0.02
Energy Slope Method= 1
Volume Change Method= 1
Sediment Retention Method= 0
XS Weighting Method= 0
Number of US Weighted Cross Sections= 1
Number of DS Weighted Cross Sections= 1
Upstream XS Weight=0
Main XS Weight=1
Downstream XS Weight=0
Number of DS XS's Weighted with US Boundary= 1
Upstream Boundary Weight= 1
Weight of XSs Associated with US Boundary= 0
Number of US XS's Weighted with DS Boundary= 1
Downstream Boundary Weight= 0.5
Weight of XSs Associated with DS Boundary= 0.5
Percentile Method= 0
Sediment Output Level= 3
Mass or Volume Output= 0
Output Increment Type= 1
Profile and TS Output Increment= 1
XS Output Flag= 0
XS Output Increment= 10
Write Gradation File= 0
Read Gradation Hotstart= 0
Write HDF5 File= 1
Write Binary Output= 1
Write DSS Sediment File= 0
SV Curve= 0
Specific Gage Flag= 0

--- WOLFPENCK.f01 (steady flow) ---

Flow Title=WV Regression w 2016/2010 Gage Weighting
Program Version=5.07
Number of Profiles= 6
Profile Names=f1p,f10p,f4p,f2p,f02p,f1pplus
River Rch & RM=WOLFPENCK,Main            ,3567
     625     332     440     530     872     925
River Rch & RM=WOLFPENCK,Main            ,2476
     726     387     513     616    1010    1070
Boundary for River Rch & Prof#=WOLFPENCK,Main            , 1
Up Type= 0
Dn Type= 3
Dn Slope=0.007917
DSS Import GetInterval= 0
DSS Import GetPeak= 0
DSS Import FillOption= 0

--- WOLFPENCK.g01 (geometry) ---

Geom Title=USGS 1m DEM
Program Version=5.07

River Reach=WOLFPENCK       ,Main
Reach XY= 30
     2029001.445      351675.853     2029074.836      351774.631
     2029130.885      351823.772     2029329.719      351904.966
     2029449.297      351991.764     2029559.114       352041.41
      2029630.42      352093.818     2029663.334      352107.546
      2029832.77      352087.246     2029916.463      352108.361
     2029962.442      352109.779     2030474.563      352037.893
     2030620.963      352005.392     2030835.634      351998.051
     2030934.969       351979.56     2030976.192       351958.49
     2031043.063      351899.991     2031135.698      351810.008
     2031211.885      351721.305     2031249.985      351642.857
     2031282.818      351509.048     2031316.331      351445.122
     2031497.019      351226.294     2031540.744      351141.887
     2031548.297       351111.83     2031580.472      351100.401
     2031599.628       351084.89     2031694.867      350961.926
     2031721.479       350869.13     2031727.818       350796.59

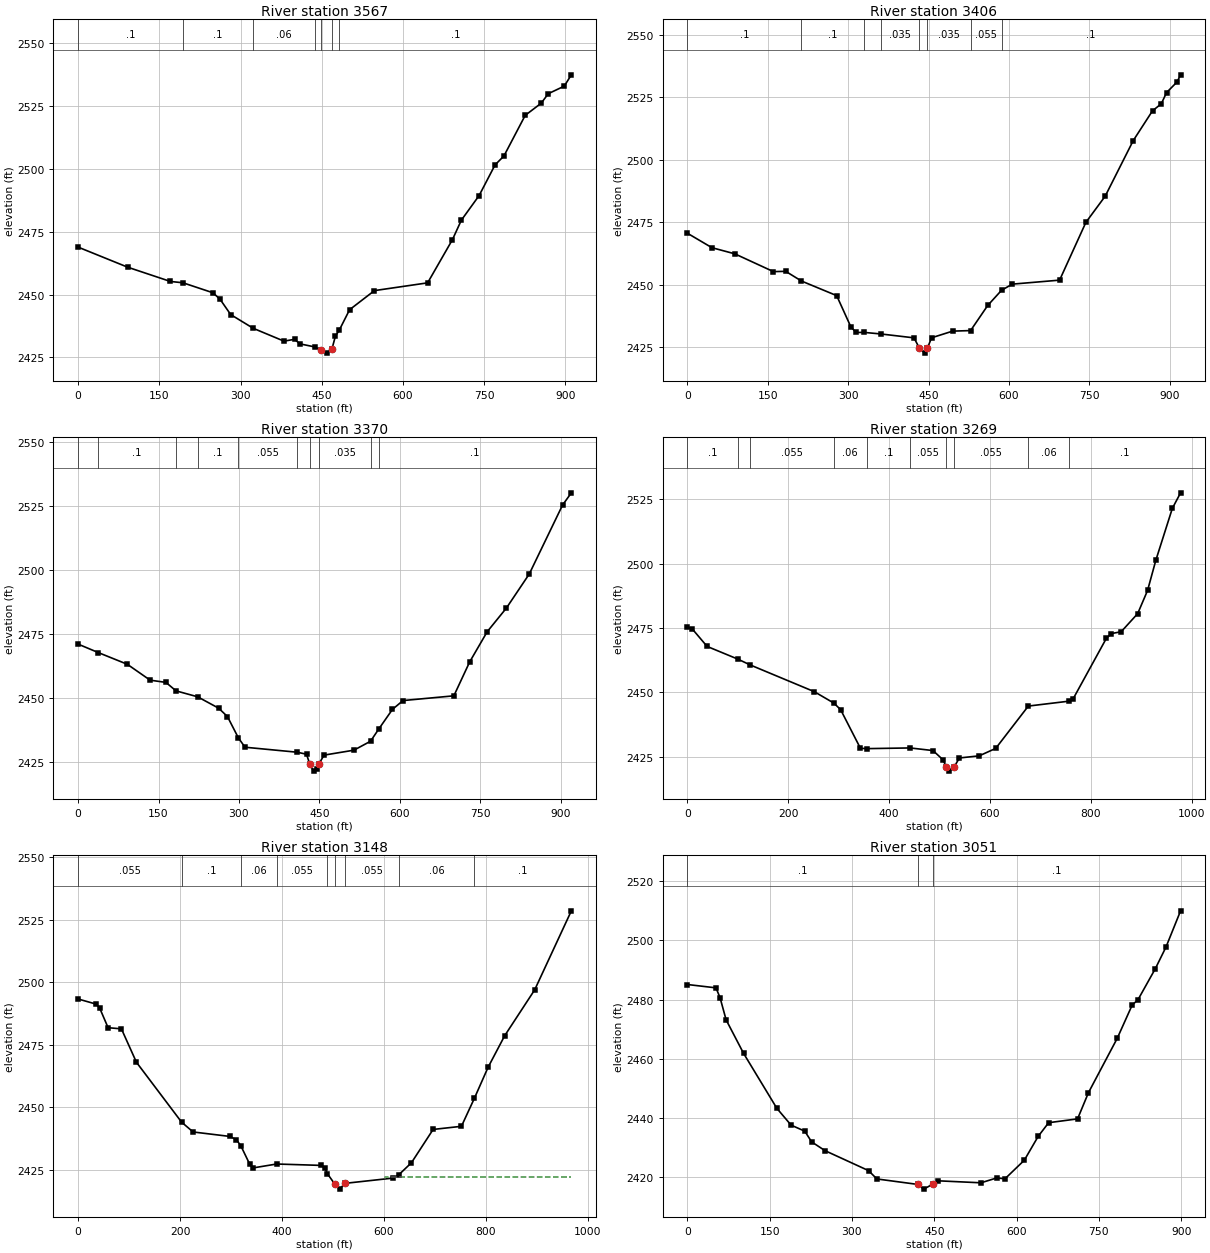
Type RM Length L Ch R = 1 ,3567    ,161.6,161.3,161.4
XS GIS Cut Line= 3
2028652.44205628351969.8639773732029007.18216045351684.029903382
2029362.15389143351398.691891372
#Sta/Elev= 30
       0 2468.93   91.77 2460.92  170.43 2455.26  193.58 2454.73  249.09 2450.75
   262.2 2448.17  281.86 2442.07  323.51  2436.6  380.19  2431.5  399.85 2432.21
  409.68 2430.41   437.8 2429.16     449 2427.82  458.84 2426.72   468.7 2428.22
  475.23 2433.46  482.54 2435.94  501.44    2444  547.31 2451.61   645.6  2454.7
  691.48 2471.94  707.86 2479.66  740.62 2489.44  770.11 2501.66  786.49 2505.21
  825.81 2521.39   855.3 2526.22  868.41 2530.01   897.9 2533.02     911 2537.52
#Mann= 7 ,-1 , 0
       0      .1       0  193.58      .1       0  323.51     .06       0
   437.8    .055       0     449    .045       0   468.7    .055       0
  482.54      .1       0
Bank Sta=449,468.7
XS Rating Curve= 0 ,0
Exp/Cntr=0.5,0.3

Type RM Length L Ch R = 1 ,3406    ,36,36.2,36.5
XS GIS Cut Line= 3
2028773.71806045352096.2259293792029146.71797059351776.122895047
2029363.75690661351406.844106048
#Sta/Elev= 30
       0 2470.67   45.88 2464.87   88.47 2462.42  160.56  2455.3   183.5 2455.41
  212.92 2451.53  278.53  2445.7  304.74 2433.31  314.57 2430.95  329.32    2431
  360.34 2430.38  422.71 2428.81  432.48 2424.85  442.37  2422.7  447.68 2424.66
  455.48 2428.83  494.79  2431.5  528.29 2431.72  560.19 2441.76  585.91 2447.82
  605.96 2450.29  694.25 2451.89  743.29    2475  779.26 2485.46  831.57  2507.7
  867.54 2519.62  883.89 2522.41   893.7  2526.9  913.32 2531.16  919.86    2534
#Mann= 8 ,-1 , 0
       0      .1       0  212.92      .1       0  329.32    .055       0
  360.34    .035       0  432.48    .045       0  447.68    .035       0
  528.29    .055       0  585.91      .1       0
#XS Ineff= 2 , 0
           417.5  2428.9  462.68          2428.9
Permanent Ineff=
       F       F
Bank Sta=432.48,447.68
XS Rating Curve= 0 ,0
Exp/Cntr=0.5,0.3

Type RM Length L Ch R = 1 ,3370    ,105.5,100.9,98.5
XS GIS Cut Line= 3
2028803.30986477352117.0798902962029176.30911876351796.976855963
2029393.34805478351427.698066965
#Sta/Elev= 30
       0 2470.95   37.73 2467.64   91.75 2463.08  134.35 2456.87  163.84    2456
  182.61  2452.7  222.93 2450.38  262.15 2445.93  278.53 2442.67  299.01 2434.31
   311.3 2430.69  408.14 2428.75  425.99 2427.97  431.77 2424.28  439.09 2421.36
  445.65 2422.31  448.88  2424.1  458.75 2427.61  514.41 2429.54  545.38 2433.03
  560.81 2437.82  586.34 2445.49  605.96 2448.91  700.78 2450.76  730.21 2463.98
  762.91 2475.78  798.88 2485.06  841.38 2498.32  903.51 2525.25  919.86 2530.01
#Mann= 10 ,-1 , 0
       0      .1       0   37.73      .1       0  182.61     .06       0
  222.93      .1       0  299.01    .055       0  408.14    .035       0
  431.77    .045       0  448.88    .035       0  545.38    .055       0
  560.81      .1       0
Bank Sta=431.77,448.88
XS Rating Curve= 0 ,0
Exp/Cntr=0.5,0.3

Type RM Length L Ch R = 1 ,3269    ,120.5,120.5,120.7
XS GIS Cut Line= 3
2028906.20696868352266.9769002052029194.40193035351945.796112135
2029430.52186494351452.822032467
#Sta/Elev= 30
       0 2475.41    9.81 2474.66   39.23 2467.87  100.56  2462.9  124.96 2460.65
  251.72 2450.29  290.65 2445.84  304.03 2443.29  343.26 2428.29  355.76 2428.15
  441.73 2428.42  487.17  2427.4  506.81 2423.86  513.82 2420.98   519.9 2419.41
  528.82 2420.96  539.54 2424.52  578.81 2425.35  611.54 2428.24  676.21 2444.69
   757.1  2446.6  765.38 2447.61  830.84 2470.97  840.66 2472.85   860.3 2473.57
  893.03  2480.6  912.67 2489.62  929.03 2501.32  961.76  2521.5  978.13 2527.55
#Mann= 10 ,-1 , 0
       0      .1       0  100.56     .06       0  124.96    .055       0
  290.65     .06       0  355.76      .1       0  441.73    .055       0
  513.82    .045       0  528.82    .055       0  676.21     .06       0
   757.1      .1       0
Bank Sta=513.82,528.82
XS Rating Curve= 0 ,0
Exp/Cntr=0.3,0.1

Type RM Length L Ch R = 1 ,3148    ,97.4,97.1,96.9
XS GIS Cut Line= 3
2029114.54086961352369.4081257882029406.20695294351787.809879541
2029512.10995637351489.198928207
#Sta/Elev= 30
       0 2493.34   35.96 2491.26    42.5 2489.64   58.85 2481.86   85.01  2481.4
  114.43 2468.05  203.06  2444.1   225.6 2440.18  297.53  2438.4   310.6 2437.09
  319.35  2434.6  336.76 2427.24   343.3 2425.81  389.56 2427.37  477.35 2426.81
  483.89  2425.9  488.95 2423.51  503.51 2419.33  513.32 2417.33  523.12 2419.63
  617.94 2421.75  629.11 2423.08   653.9 2427.89  696.36 2441.19  751.89 2442.44
   777.4 2453.69  804.15 2466.03  836.81 2478.68  895.61 2497.01  967.47 2528.58
#Mann= 9 ,-1 , 0
       0    .055       0  203.06      .1       0  319.35     .06       0
  389.56    .055       0  488.95     .05       0  503.51    .045       0
  523.12    .055       0  629.11     .06       0   777.4      .1       0
#XS Ineff= 2 , 0
                          602.45         2422.32
Permanent Ineff=
       F       F
Bank Sta=503.51,523.12
XS Rating Curve= 0 ,0
Exp/Cntr=0.3,0.1

Type RM Length L Ch R = 1 ,3051    ,83.8,84,84.4
XS GIS Cut Line= 4
2029231.51689813352361.9184926042029334.77472651352164.007654863
2029538.42211027351707.9522461572029587.18275146351538.724138524
#Sta/Elev= 30
       0 2485.12    52.2 2483.99    59.6  2480.7    70.7 2473.17   102.4 2461.88
   163.2 2443.25   189.1 2437.58     214 2435.54   226.5 2431.92     251 2428.94
   330.3 2422.19   345.4 2419.38   419.6 2417.54   430.9 2415.94   447.3 2417.63
     456 2418.76   535.1 2418.08     564 2419.73   578.9 2419.44   614.1 2425.72
   639.3 2433.77   658.4  2438.4   711.1 2439.69   730.9 2448.54   783.4 2466.94
   810.7 2478.21     821 2479.92   852.9 2490.51   872.2 2497.78   898.8 2510.03
#Mann= 3 , 0 , 0
       0      .1       0   419.6    .045       0   447.3      .1       0
Bank Sta=419.6,447.3
XS Rating Curve= 0 ,0
Exp/Cntr(USF)=0,0
Exp/Cntr=0.3,0.1

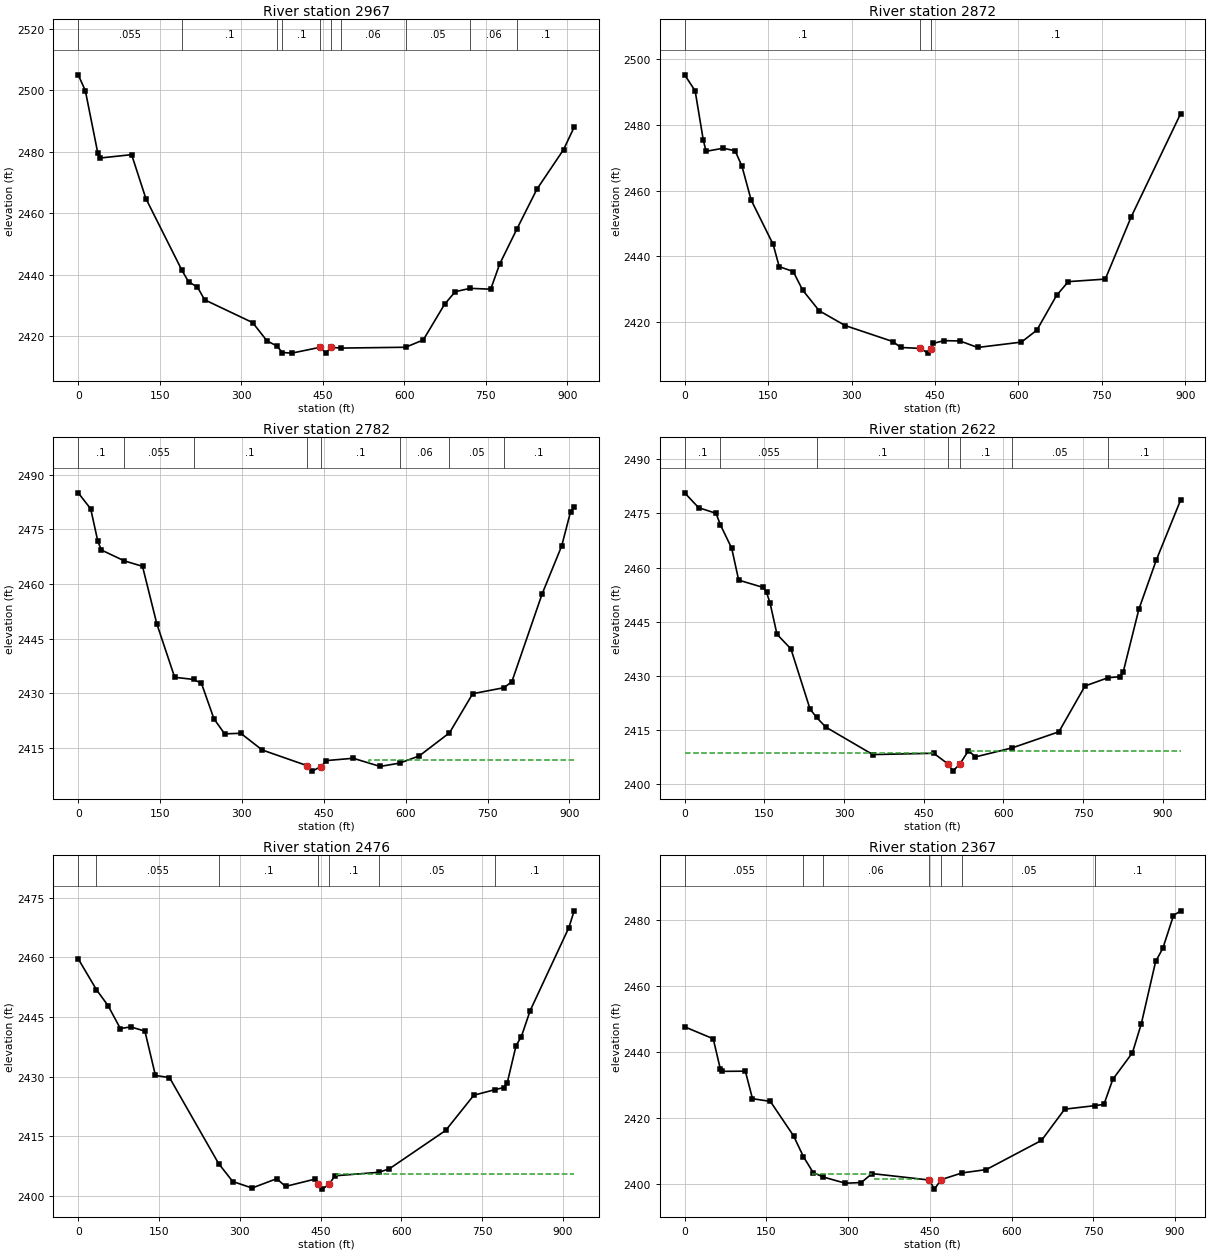
Type RM Length L Ch R = 1 ,2967    ,92.6,95.3,91.6
XS GIS Cut Line= 3
2029296.42305176352423.1931232072029493.44693594352012.678852379
2029694.12107526  351601.8210783
#Sta/Elev= 30
       0 2505.04    13.1  2499.9   36.03  2479.6   39.31 2477.97   98.28 2479.09
  124.48 2464.83  190.93 2441.45   203.1 2437.75  219.48 2436.02  232.59  2431.9
  321.04 2424.48  347.24 2418.57  365.03 2416.92  375.81 2414.76   393.1 2414.56
  445.52 2416.47  455.35 2414.58  465.14 2416.44  483.49  2416.2  602.38 2416.47
  634.98 2418.85  674.17 2430.44  693.77 2434.54  721.27 2435.62  759.09 2435.35
  775.42 2443.48  807.01 2454.84  844.01 2467.84     893  2480.7  912.59 2488.03
#Mann= 10 ,-1 , 0
       0    .055       0  190.93      .1       0  365.03     .05       0
  375.81      .1       0  445.52    .045       0  465.14      .1       0
  483.49     .06       0  602.38     .05       0  721.27     .06       0
  807.01      .1       0
Bank Sta=445.52,465.14
XS Rating Curve= 0 ,0
Exp/Cntr=0.3,0.1

Type RM Length L Ch R = 1 ,2872    ,90.3,89.9,89.5
XS GIS Cut Line= 4
2029400.74500576352450.8349559372029532.68556425352158.271108842
2029687.57230683351779.659071425  2029733.464675351624.772328846
#Sta/Elev= 30
       0 2495.28    18.8  2490.4    33.5 2475.37    38.5    2472    69.2 2472.94
    90.7 2472.17     103 2467.42   119.5 2457.17   159.1 2443.65   169.9 2436.91
   195.1 2435.42   212.1 2429.76   241.9 2423.47   288.7 2418.96   374.3  2414.1
   388.4  2412.3   423.9 2412.02     437 2410.58     442 2411.94     447 2413.55
   466.4 2414.38   494.9 2414.28   526.7  2412.3   605.5 2413.94   633.2 2417.59
   668.5 2428.13   689.7 2432.34   756.2 2433.11   802.6    2452   891.6 2483.46
#Mann= 3 , 0 , 0
       0      .1       0   423.9    .045       0     442      .1       0
Bank Sta=423.9,442
XS Rating Curve= 0 ,0
Exp/Cntr(USF)=0,0
Exp/Cntr=0.3,0.1

Type RM Length L Ch R = 1 ,2782    ,162.5,160,159.4
XS GIS Cut Line= 3
2029498.22087653352508.2959713792029713.49898927351931.908016548
2029769.05399628351643.713054881
#Sta/Elev= 30
       0 2485.07   22.91 2480.66      36 2471.72   42.55 2469.36   84.36 2466.39
  117.82 2464.89     144 2449.13  176.73 2434.42  211.27 2433.83  225.82 2432.76
  248.73 2423.02  268.37 2418.88  297.82 2419.04  337.09 2414.46  418.91 2410.18
  428.73 2408.65  445.09 2409.92  454.91 2411.55     504 2412.18   553.1 2409.94
  589.11 2410.85  625.06 2412.84  680.35 2419.17   722.9 2429.91  780.43 2431.57
  794.64 2433.21  850.08 2457.31  885.95 2470.48  902.26 2479.92  908.78 2481.13
#Mann= 8 ,-1 , 0
       0      .1       0   84.36    .055       0  211.27      .1       0
  418.91    .045       0  445.09      .1       0  589.11     .06       0
  680.35     .05       0  780.43      .1       0
#XS Ineff= 2 , 0
                          532.61         2411.59
Permanent Ineff=
       F       F
Bank Sta=418.91,445.09
XS Rating Curve= 0 ,0
Exp/Cntr=0.3,0.1

Type RM Length L Ch R = 1 ,2622    ,150,146.4,147.3
XS GIS Cut Line= 3
2029670.09586085352570.7958463732029803.77702393352141.977150217
2029835.51186861351658.536844134
#Sta/Elev= 30
       0 2480.72   26.23  2476.6   59.02 2475.05   67.15 2471.88   88.52 2465.36
  101.64 2456.53  147.54 2454.51   154.1 2453.13  160.65 2450.22  173.77 2441.52
     200 2437.46  236.06 2420.78  248.41 2418.46  265.57  2415.8  354.09 2408.18
  468.81 2408.54  496.56 2405.49  504.82 2403.59  517.93 2405.52  534.28 2409.27
  547.38 2407.53  617.15 2410.06  704.51 2414.49  753.61 2427.18  797.02 2429.48
  819.08 2429.75  825.63 2431.11  855.09 2448.47  887.82 2462.07  933.65 2478.72
#Mann= 7 ,-1 , 0
       0      .1       0   67.15    .055       0  248.41      .1       0
  496.56    .045       0  517.93      .1       0  617.15     .05       0
  797.02      .1       0
#XS Ineff= 2 , 0
          469.32  2408.6  534.61         2409.25
Permanent Ineff=
       F       F
Bank Sta=496.56,517.93
XS Rating Curve= 0 ,0
Exp/Cntr=0.3,0.1

Type RM Length L Ch R = 1 ,2476    ,110.1,108.4,109.2
XS GIS Cut Line= 3
2029949.61006559352570.7958463732029965.23503436352313.852134541
 2029916.6239111351652.394139871
#Sta/Elev= 30
       0 2459.64   33.92 2451.86   55.39 2447.86    78.2 2442.09   97.75  2442.5
  123.82 2441.43  143.37 2430.27  169.44 2429.74  260.75 2408.06  286.82 2403.57
  322.76 2401.93   368.5 2404.28  384.84 2402.33  440.38  2404.2  446.05 2403.01
  453.45 2401.65  466.48 2402.97  476.32    2405  557.95 2405.89   577.6 2406.77
  682.15 2416.43  734.43  2425.3   773.2 2426.68  789.97 2427.23  796.51 2428.45
  812.84  2437.8  822.64 2440.05  838.98 2446.59  910.86 2467.51  920.66 2471.73
#Mann= 7 ,-1 , 0
       0      .1       0   33.92    .055       0  260.75      .1       0
  446.05    .045       0  466.48      .1       0  557.95     .05       0
   773.2      .1       0
#XS Ineff= 2 , 0
                          480.95         2405.49
Permanent Ineff=
       F       F
Bank Sta=446.05,466.48
XS Rating Curve= 0 ,0
Exp/Cntr=0.5,0.3

Type RM Length L Ch R = 1 ,2367    ,41.9,41.9,42.1
XS GIS Cut Line= 3
 2030115.8479221352544.3041014672030057.14790829  352092.9578913
2030002.18509169 351641.31804654
#Sta/Elev= 30
       0 2447.65   52.39 2444.04   65.49 2434.84   68.76 2434.18  111.33 2434.24
  124.43 2425.91  157.17  2425.1  199.74 2414.69  217.96 2408.36  235.76 2403.56
  254.32 2402.21   294.7 2400.34  324.17 2400.54  343.82 2403.25  448.61 2401.31
  458.42 2398.55  470.39  2401.4  508.83 2403.45  553.34 2404.45  654.81 2413.29
  697.36 2422.74   753.8 2423.83  769.37 2424.19  785.74 2431.79  821.74 2439.82
  838.11 2448.66  864.29 2467.44  877.39 2471.37  897.03 2481.33  910.12 2482.75
#Mann= 7 ,-1 , 0
       0    .055       0  217.96      .1       0  254.32     .06       0
  448.61    .045       0  470.39     .06       0  508.83     .05       0
   753.8      .1       0
#XS Ineff= 3 ,-1
  233.85   344.12403.268  347.83  430.792401.641   490.4     600  2401.7
Permanent Ineff=
       F       F       F
Bank Sta=448.61,470.39
XS Rating Curve= 0 ,0
Exp/Cntr=0.5,0.3

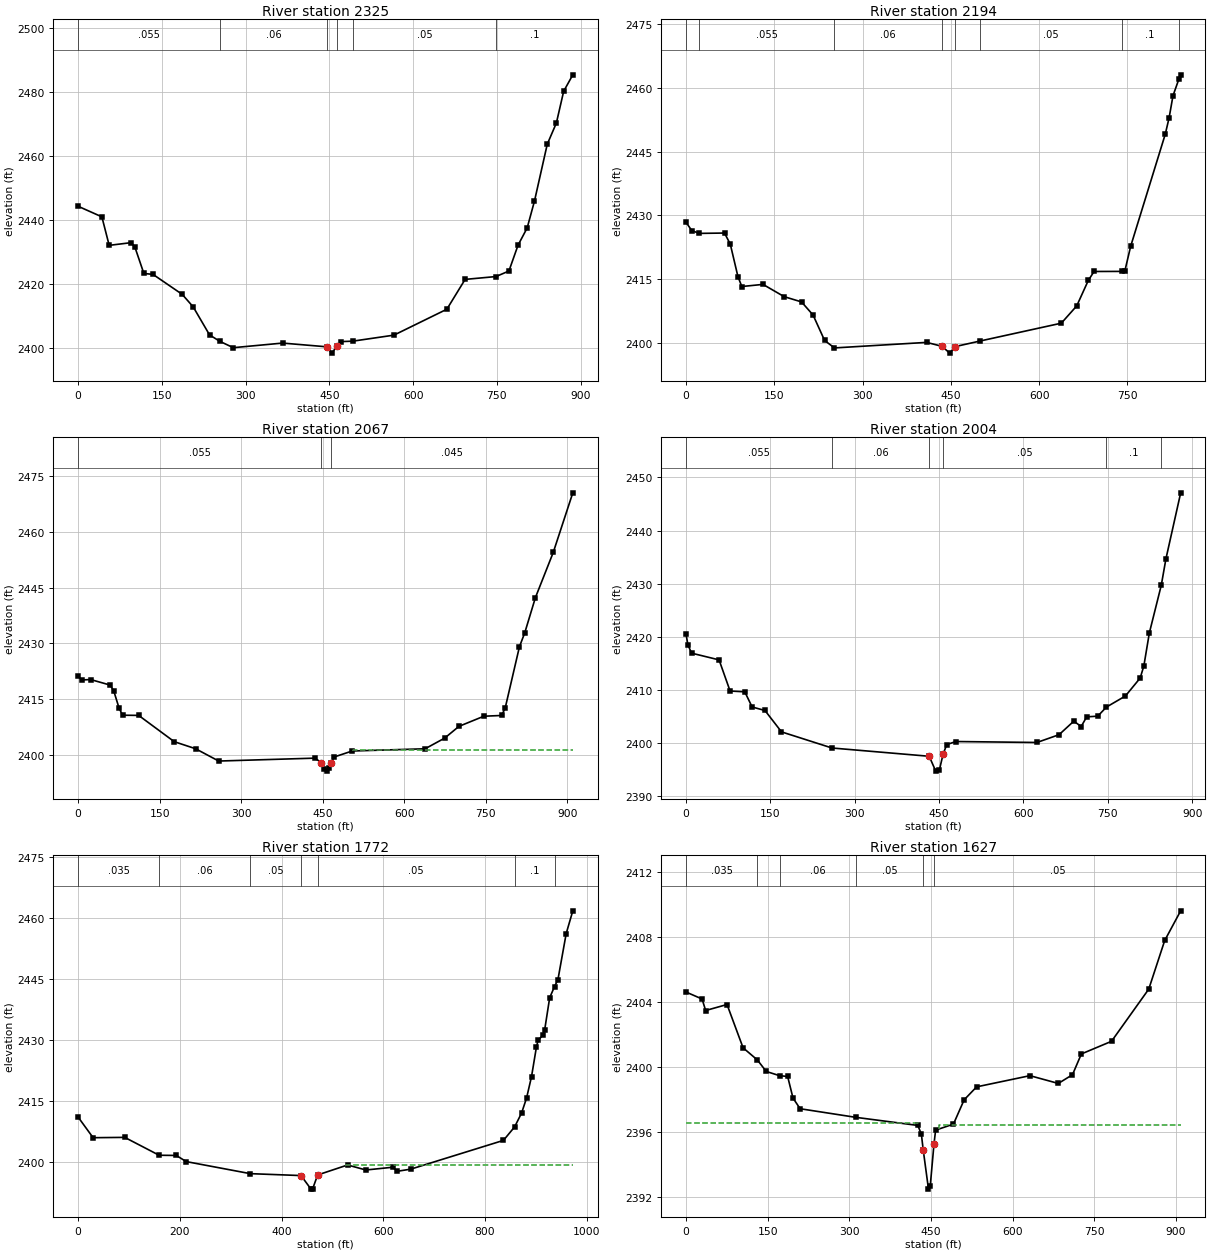
Type RM Length L Ch R = 1 ,2325    ,131.4,131.4,131.1
XS GIS Cut Line= 2
2030154.86063935352537.7998493762030045.13841785351658.633300632
#Sta/Elev= 30
       0 2444.39    42.5 2441.09   55.58 2432.18   94.81 2433.02  101.35 2431.78
   117.7 2423.39  134.04 2423.11  186.35 2416.87  205.97 2412.97  235.39 2404.19
  253.94 2402.17  277.89  2400.2  366.16 2401.64  445.61 2400.47  454.44  2398.5
  464.24 2400.87  470.78  2402.1  491.88 2402.24  565.59 2404.12   660.4 2412.22
   693.1 2421.54  748.37 2422.43  771.56 2424.16  787.91 2432.24  804.25 2437.63
  817.33 2446.02  840.22 2463.78  856.56 2470.42  869.64 2480.34  885.99 2485.47
#Mann= 6 ,-1 , 0
       0    .055       0  253.94     .06       0  445.61    .045       0
  464.24     .06       0  491.88     .05       0  748.37      .1       0
Bank Sta=445.61,464.24
XS Rating Curve= 0 ,0
Exp/Cntr=0.5,0.3

Type RM Length L Ch R = 1 ,2194    ,126.1,126.7,126.9
XS GIS Cut Line= 2
2030286.80492927352515.5777809622030177.08270778351682.244473875
#Sta/Elev= 30
       0 2428.41    9.81 2426.45   22.63  2425.8   65.41 2425.88   75.22 2423.27
    88.3 2415.61   94.85 2413.33  130.82 2413.83   166.8 2410.95  196.23 2409.72
  215.85 2406.65  235.48 2400.67  252.27 2398.92  408.82 2400.22  434.98  2399.3
  448.06  2397.7  457.87 2399.25  500.21 2400.56  637.75 2404.73  663.92 2408.79
  683.54 2414.76  693.35 2416.86  739.97 2416.88  745.68    2417  755.49 2422.75
  814.36 2449.09   820.9 2452.95  827.44 2458.09  837.51 2462.03  840.53 2463.01
#Mann= 8 ,-1 , 0
       0    .035       0   22.63    .055       0  252.27     .06       0
  434.98    .045       0  457.87     .06       0  500.21     .05       0
  739.97      .1       0  837.51      .1       0
Bank Sta=434.98,457.87
XS Rating Curve= 0 ,0
Exp/Cntr=0.5,0.3

Type RM Length L Ch R = 1 ,2067    ,64.7,63.2,63.3
XS GIS Cut Line= 3
2030397.64985193352504.6998499632030352.47999476352051.946162298
2030307.31013761351599.196083546
#Sta/Elev= 30
       0 2421.19    6.55 2420.18   22.91  2420.3   58.92 2418.81   65.47 2417.26
   75.29 2412.61   81.83 2410.71   111.3 2410.66  176.76  2403.6  216.04  2401.7
   258.6 2398.39  435.36 2399.17   447.5 2397.99  451.73 2396.35  456.99 2395.68
  461.55  2396.4   464.8 2397.94  471.37  2399.5   504.1 2401.09  638.31 2401.69
  674.32 2404.56   700.5 2407.71  746.33 2410.44  779.06 2410.64  785.61 2412.64
   811.8  2429.1  821.62 2432.87  841.26 2442.35  873.99 2454.46     910 2470.49
#Mann= 3 ,-1 , 0
       0    .055       0   447.5    .045       0   464.8    .045       0
#XS Ineff= 2 , 0
                          505.92         2401.45
Permanent Ineff=
       F       F
Bank Sta=447.5,464.8
XS Rating Curve= 0 ,0
Exp/Cntr=0.5,0.3

Type RM Length L Ch R = 1 ,2004    ,232.4,232.5,233.8
XS GIS Cut Line= 3
2030465.97156568352494.7444892972030410.41590251352001.688716874
2030364.58266087 351621.13337563
#Sta/Elev= 30
       0 2420.48    3.26  2418.5    9.79 2416.89   58.76 2415.62   78.34 2409.75
  104.46  2409.6  117.52 2406.74  140.37 2406.08  169.74 2402.05  259.47 2399.01
  432.36 2397.45  443.95 2394.65  450.48 2394.87     457 2397.82  463.53 2399.65
  479.85 2400.23  623.94 2400.05  663.26 2401.52  689.47 2404.07  702.57 2403.06
   712.4 2404.88  732.06 2405.01  747.39 2406.72   781.2 2408.81  807.41 2412.19
  813.96 2414.46  823.79 2420.71  844.96 2429.68  853.27 2434.68  879.48 2447.11
#Mann= 6 ,-1 , 0
       0    .055       0  259.47     .06       0  432.36    .045       0
     457     .05       0  747.39      .1       0  844.96      .1       0
Bank Sta=432.36,457
XS Rating Curve= 0 ,0
Exp/Cntr=0.5,0.3

Type RM Length L Ch R = 1 ,1772    ,144.2,144.5,145.3
XS GIS Cut Line= 3
2030690.06691803352457.1061131212030619.74914528351770.449021876
2030461.76291268351536.074162543
#Sta/Elev= 30
       0 2411.04   29.44 2405.99    91.6 2406.07  159.29 2401.68  193.01 2401.63
  212.64 2400.12  338.58 2397.16  438.36 2396.69  457.98 2393.36  461.25 2393.45
  471.07 2396.84  529.95 2399.29  565.94 2398.06  618.28 2398.73  628.09 2397.75
  654.26 2398.27  836.45 2405.33  858.52 2408.66  872.18 2412.06  881.93 2415.73
  891.68 2420.98  901.42 2428.31  904.67 2429.93  914.42 2431.22  917.67 2432.56
  927.41 2440.37  937.01 2443.12  943.66 2444.83   959.9 2456.13   972.9 2461.71
#Mann= 7 ,-1 , 0
       0    .035       0  159.29     .06       0  338.58     .05       0
  438.36    .045       0  471.07     .05       0  858.52      .1       0
  937.01      .1       0
#XS Ineff= 2 , 0
                          526.73         2399.26
Permanent Ineff=
       F       F
Bank Sta=438.36,471.07
XS Rating Curve= 0 ,0
Exp/Cntr=0.5,0.3

Type RM Length L Ch R = 1 ,1627    ,29.1,29.1,29.6
XS GIS Cut Line= 3
2030836.13814817352445.5559393762030774.94010787351879.148935705
2030681.18996726351553.628917456
#Sta/Elev= 30
       0 2404.62   29.47 2404.19   36.02 2403.48   75.31 2403.85  104.77 2401.18
  131.01 2400.43  147.34 2399.72  171.75 2399.46  186.63 2399.41  196.45 2398.08
  209.55 2397.42   311.6 2396.89  425.64 2396.39  432.19 2395.86  435.53  2394.9
  445.29 2392.46  448.56 2392.67  455.33 2395.22  458.38  2396.1  491.12 2396.47
  510.77 2397.97  533.69 2398.77  631.59 2399.46  683.71 2398.98  709.77 2399.52
  726.05  2400.8  781.42 2401.58  849.83  2404.8  879.14  2407.8  908.46 2409.63
#Mann= 6 ,-1 , 0
       0    .035       0  131.01    .055       0  171.75     .06       0
   311.6     .05       0  435.53    .045       0  455.33     .05       0
#XS Ineff= 2 , 0
          425.62 2396.52  465.35         2396.43
Permanent Ineff=
       F       F
Bank Sta=435.53,455.33
XS Rating Curve= 0 ,0
Exp/Cntr=0.5,0.3

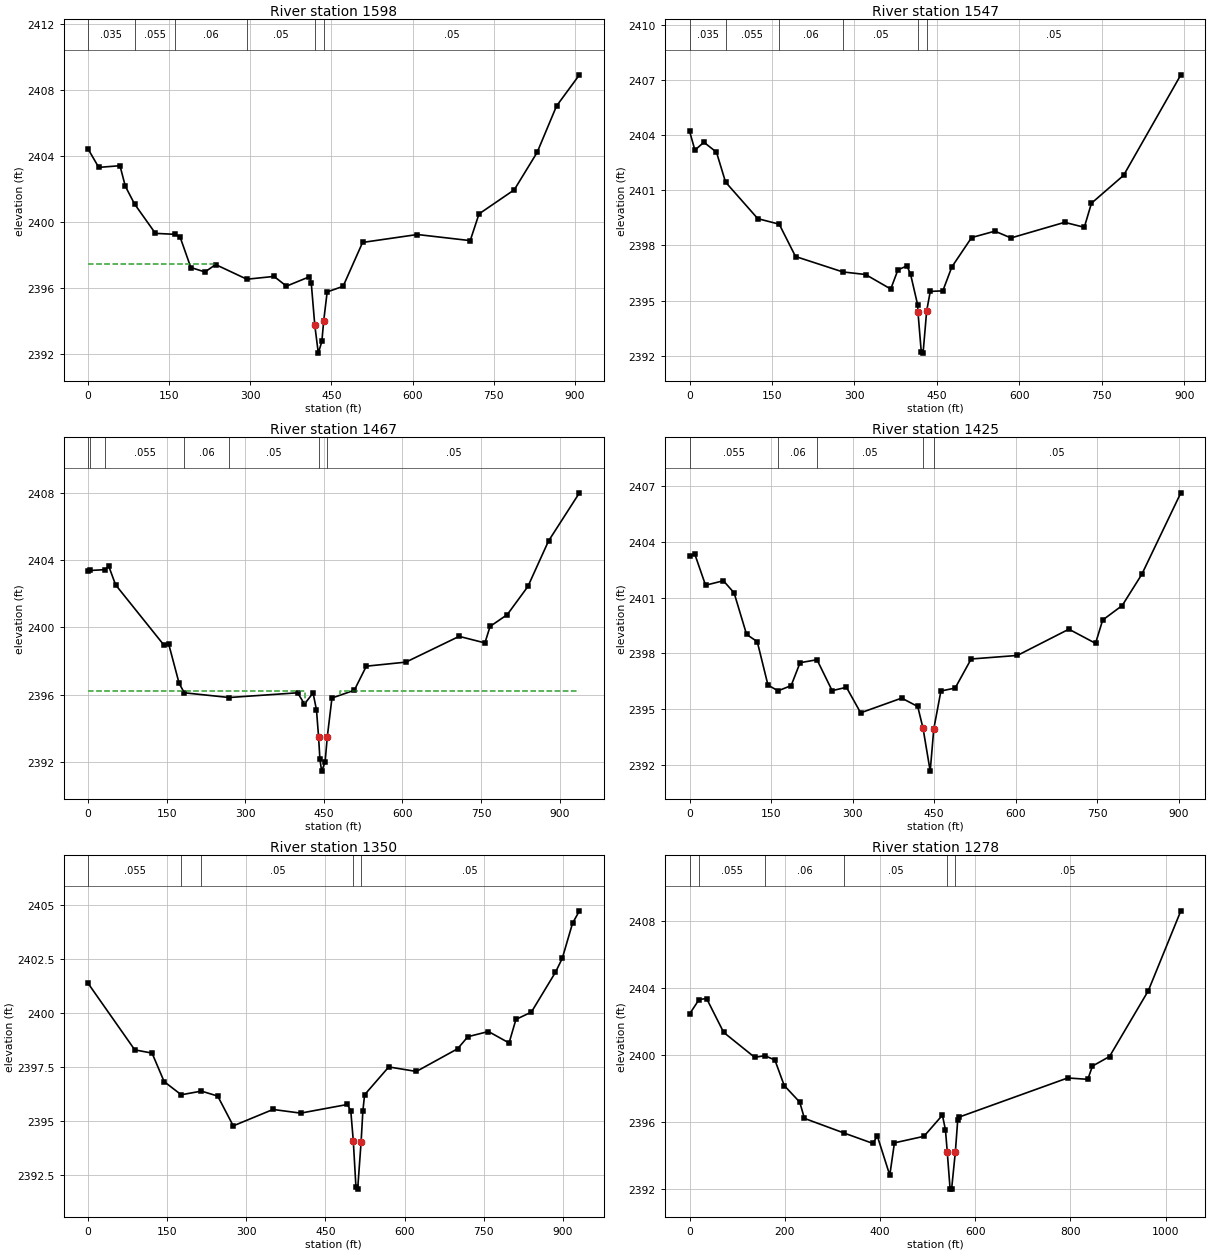
Type RM Length L Ch R = 1 ,1598    ,51.8,51.2,50.9
XS GIS Cut Line= 3
2030863.48094128352428.6291359662030802.28290094351862.222132295
2030708.53308843351536.702114046
#Sta/Elev= 30
       0 2404.43   19.64 2403.32   58.93 2403.42   68.76 2402.18   85.87  2401.1
  124.42 2399.32  161.32 2399.26  170.26 2399.08   189.9 2397.25  216.09 2396.98
  235.74 2397.43   293.5 2396.54  343.79 2396.71  366.71 2396.12  409.27 2396.69
  412.54 2396.33  419.13 2393.75  425.64 2392.06  432.19 2392.77  435.53    2394
  442.01 2395.77  471.48 2396.11   507.5 2398.77  608.79 2399.25  706.51 2398.88
  722.79  2400.5  787.94 2401.96  830.28 2404.23  866.11 2407.04  908.46 2408.93
#Mann= 6 ,-1 , 0
       0    .035       0   85.87    .055       0  161.32     .06       0
   293.5     .05       0  419.13    .045       0  435.53     .05       0
#XS Ineff= 2 , 0
          236.18 2397.45
Permanent Ineff=
       F       F
Bank Sta=419.13,435.53
XS Rating Curve= 0 ,0
Exp/Cntr=0.5,0.3

Type RM Length L Ch R = 1 ,1547    ,81.4,79.5,77.6
XS GIS Cut Line= 3
2030938.19371836352414.1888761222030849.30478851351882.244401962
2030728.47169687351548.911079124
#Sta/Elev= 30
       0 2404.23    9.81 2403.19   26.15 2403.62   49.03 2403.08   65.58 2401.45
  124.21 2399.46  163.18 2399.16  192.85  2397.4  278.96 2396.56  320.32 2396.42
  366.08 2395.63  379.16 2396.67   395.5 2396.89  402.04 2396.45  415.11 2394.76
  415.55  2394.4  421.65  2392.2  424.92 2392.14  431.46 2394.44  437.99  2395.5
  460.87 2395.53  477.22 2396.83  513.17 2398.43  555.58 2398.78  584.86 2398.41
  682.45 2399.26  718.23 2398.99  731.24  2400.3  789.79 2401.82  893.88 2407.29
#Mann= 6 ,-1 , 0
       0    .035       0   65.58    .055       0  163.18     .06       0
  278.96     .05       0  415.55    .045       0  431.46     .05       0
Bank Sta=415.55,431.46
XS Rating Curve= 0 ,0
Exp/Cntr=0.5,0.3

Type RM Length L Ch R = 1 ,1467    ,42.4,42.4,42.4
XS GIS Cut Line= 3
2031108.02408735352394.3778921222030945.22585653351975.910881296
2030736.22693069351534.077119291
#Sta/Elev= 30
       0 2403.32    3.28 2403.38   32.67 2403.43   39.33 2403.64   52.44 2402.53
  144.21 2398.97  154.04 2398.99  173.71 2396.68   183.6 2396.12  269.33 2395.84
  399.86 2396.12  412.97 2395.45  429.35 2396.11  435.91  2395.1  439.85 2393.51
  442.46 2392.17  445.74 2391.47   452.3    2392   456.5  2393.5  465.42 2395.81
  508.06 2396.27  531.03  2397.7  606.48 2397.94  708.17 2399.47  757.37 2399.08
  767.21 2400.06  800.02 2400.76  839.38 2402.43  878.75 2405.13  937.79 2407.99
#Mann= 7 ,-1 , 0
       0    .055       0    3.28    .035       0   32.67    .055       0
   183.6     .06       0  269.33     .05       0  439.85    .045       0
   456.5     .05       0
#XS Ineff= 2 , 0
          414.85  2396.2   481.5          2396.2
Permanent Ineff=
       F       F
Bank Sta=439.85,456.5
XS Rating Curve= 0 ,0
Exp/Cntr=0.5,0.3

Type RM Length L Ch R = 1 ,1425    ,77.9,74.4,73.7
XS GIS Cut Line= 3
2031160.41604294352360.0219897182030963.19366835351912.799787045
2030763.19374026351548.911079124
#Sta/Elev= 30
       0 2403.25    9.84 2403.32   29.52 2401.66   62.33  2401.9   82.01 2401.25
  104.97 2399.02  124.65 2398.63  144.34  2396.3  162.86 2395.99  186.98 2396.27
  203.38  2397.5  234.56 2397.66  262.43    2396  288.67 2396.18  314.92 2394.81
  390.37  2395.6  419.89 2395.15  429.73 2393.97  442.85 2391.68  449.41 2393.94
  462.54 2395.98  488.78 2396.14   518.2  2397.7  603.21 2397.89  698.03  2399.3
  747.07 2398.54  760.15 2399.79  796.11 2400.57  832.08 2402.24  904.01 2406.62
#Mann= 5 ,-1 , 0
       0    .055       0  162.86     .06       0  234.56     .05       0
  429.73    .045       0  449.41     .05       0
Bank Sta=429.73,449.41
XS Rating Curve= 0 ,0
Exp/Cntr=0.5,0.3

Type RM Length L Ch R = 1 ,1350    ,70.9,72.6,74.2
XS GIS Cut Line= 3
2031317.36061095352329.4666046352030981.24940653351821.133303717
2030786.80491354351564.188935712
#Sta/Elev= 30
       0 2401.39   88.46 2398.31  121.23 2398.16  144.16 2396.84   176.6 2396.23
  214.81  2396.4  245.73 2396.17  275.21 2394.79  350.57 2395.55  402.99 2395.38
  491.45 2395.78  498.01  2395.5  502.81  2394.1  507.84 2391.96  511.11 2391.86
  517.67 2394.06  520.94 2395.47  524.22 2396.23  570.09 2397.52  622.42 2397.31
  700.54 2398.36  720.07 2398.92  759.12 2399.16  798.18 2398.63   811.2 2399.72
  840.49 2400.06  886.06  2401.9  899.08 2402.55  918.61 2404.18  931.63 2404.75
#Mann= 5 ,-1 , 0
       0    .055       0   176.6     .06       0  214.81     .05       0
  502.81    .045       0  517.67     .05       0
Bank Sta=502.81,517.67
XS Rating Curve= 0 ,0
Exp/Cntr=0.5,0.3

Type RM Length L Ch R = 1 ,1278    ,34.4,36.3,35.6
XS GIS Cut Line= 4
 2031442.6999272352273.3679635382031106.76293503351895.764059961
2031070.30401842351809.8268958782030749.99199502351518.160156384
#Sta/Elev= 30
       0 2402.45   20.11 2403.32   35.87 2403.38   71.74 2401.36  136.95 2399.87
   158.3 2399.97  179.34 2399.71   198.9 2398.19  231.51  2397.2  241.29 2396.23
  325.18 2395.35  384.76 2394.74  394.54 2395.17  420.63 2392.84  430.41 2394.77
  492.37 2395.16  531.16 2396.42   537.6 2395.54  541.28 2394.25  547.26 2392.03
  550.48 2392.01  558.39 2394.24  563.35 2396.14  566.57 2396.31  794.19 2398.64
  836.53 2398.56  846.31 2399.35  882.14 2399.92  963.56 2403.84 1031.97 2408.61
#Mann= 6 ,-1 , 0
       0    .035       0   20.11    .055       0   158.3     .06       0
  325.18     .05       0  541.28    .045       0  558.39     .05       0
#XS Ineff= 2 , 0
          524.11 2395.46  574.22         2395.43
Permanent Ineff=
       F       F
Bank Sta=541.28,558.39
XS Rating Curve= 0 ,0
Exp/Cntr=0.5,0.3

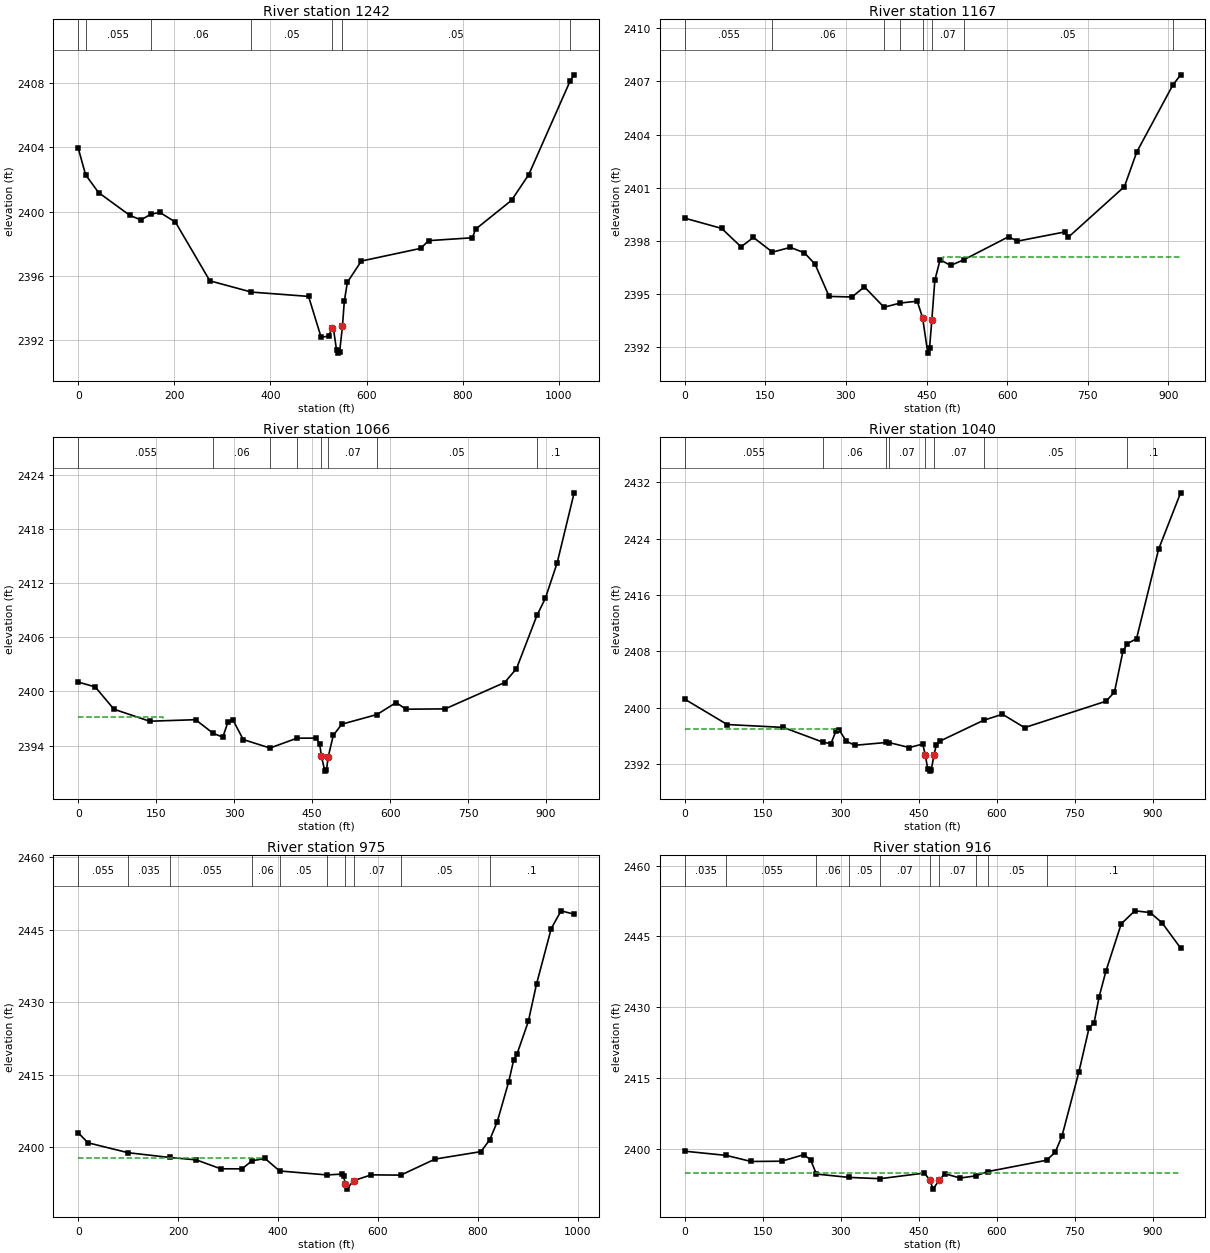
Type RM Length L Ch R = 1 ,1242    ,80.5,74.3,70.8
XS GIS Cut Line= 4
2031466.13787244352242.1180260482031130.19989602351864.514122456
 2031093.7419637351778.5769583732030773.42895602351486.909890801
#Sta/Elev= 30
       0 2403.96   15.36  2402.3   42.39 2401.19   107.6 2399.77  130.43 2399.49
  150.85 2399.84  169.56 2399.96  202.16 2399.36   273.9  2395.7  360.22    2395
  479.32 2394.73  505.41 2392.19   521.5 2392.26  527.88 2392.78  531.16  2392.7
   537.6 2391.38  540.82  2391.2  544.04  2391.3  549.88 2392.88  553.69 2394.43
  560.13 2395.61   589.1 2396.93  712.76 2397.72  729.05  2398.2  820.25 2398.38
  826.76 2398.91  901.68 2400.71  937.51 2402.31 1023.51 2408.13 1031.97 2408.52
#Mann= 7 ,-1 , 0
       0    .035       0   15.36    .055       0  150.85     .06       0
  360.22     .05       0  527.88    .045       0  549.88     .05       0
 1023.51      .1       0
Bank Sta=527.88,549.88
XS Rating Curve= 0 ,0
Exp/Cntr=0.5,0.3

Type RM Length L Ch R = 1 ,1167    ,106.1,101.4,99
XS GIS Cut Line= 3
2031502.36188136352079.343089134 2031166.6059912351776.291857958
2030803.10212503351477.866929874
#Sta/Elev= 30
       0 2399.28   68.83  2398.7  104.88 2397.66  127.82 2398.19  163.35 2397.36
  196.65 2397.63  222.87 2397.32  242.54 2396.68  268.76 2394.86  311.36 2394.83
  334.31  2395.4  370.86 2394.25  401.32 2394.49  432.63 2394.59   442.5 2393.67
   452.3 2391.66  455.56 2391.96   459.8 2393.54  465.36 2395.77  475.16 2396.93
  494.75 2396.61  519.34 2396.93  602.53 2398.23  618.86 2397.98  707.05  2398.5
  713.58  2398.2  818.09 2401.06  840.95 2403.01  907.93 2406.78  922.61 2407.37
#Mann= 8 ,-1 , 0
       0    .055       0  163.35     .06       0  370.86     .05       0
  401.32     .07       0   442.5    .045       0   459.8     .07       0
  519.34     .05       0  907.93      .1       0
#XS Ineff= 2 , 0
                          479.96         2397.07
Permanent Ineff=
       F       F
Bank Sta=442.5,459.8
XS Rating Curve= 0 ,0
Exp/Cntr=0.5,0.3

Type RM Length L Ch R = 1 ,1066    ,25.9,25.4,25
XS GIS Cut Line= 4
2031582.02313934352002.5348437882031270.82494284351703.056112051
2031174.47113295351686.1289805472030834.62699635351432.222008049
#Sta/Elev= 30
       0 2401.04   32.72  2400.5   68.71 2398.03  137.42  2396.7  225.76 2396.87
  259.34 2395.37  278.11 2394.93  287.93  2396.6  297.74 2396.83  317.38 2394.67
  368.88 2393.73  420.72 2394.82  457.98 2394.83   464.5 2394.14  467.82 2392.84
  474.29 2391.17  477.55 2391.31  480.82 2392.74  490.59 2395.12   506.9 2396.37
  574.54 2397.44   611.3 2398.76  630.88 2398.03  705.94 2398.07  820.15 2400.99
  842.99 2402.52  882.33 2408.42  898.47 2410.31  921.31 2414.26  953.94 2422.01
#Mann= 8 ,-1 , 0
       0    .055       0  259.34     .06       0  368.88     .05       0
  420.72     .07       0  467.82    .045       0  480.82     .07       0
  574.54     .05       0  882.33      .1       0
#XS Ineff= 2 , 0
          162.58 2397.16   490.1         2394.96
Permanent Ineff=
       F       F
Bank Sta=467.82,480.82
XS Rating Curve= 0 ,0
Exp/Cntr=0.5,0.3

Type RM Length L Ch R = 1 ,1040    ,64.1,65.7,66.8
XS GIS Cut Line= 4
 2031589.8351316351979.0968985412031278.63791935351679.617838711
2031182.28312518  351662.69103532030842.43997286351408.785047039
#Sta/Elev= 30
       0 2401.21    81.8  2397.6  189.77 2397.19  266.42 2395.08  281.38 2394.89
   291.2 2396.72  297.74 2396.76  310.83 2395.23  327.19 2394.65  387.98 2395.05
  393.14 2395.04  431.89 2394.33  457.98 2394.83  462.84 2393.22  467.76 2391.22
  471.02 2390.98  474.29 2391.12  479.36 2393.23  484.07 2394.73  490.59 2395.23
  574.88  2398.2   611.3 2399.06  653.72 2397.16  810.36 2400.91  826.68  2402.2
  842.99 2408.01  851.62  2409.1   869.1 2409.79  911.52 2422.49  953.94 2430.52
#Mann= 8 ,-1 , 0
       0    .055       0  266.42     .06       0  387.98     .05       0
  393.14     .07       0  462.84    .045       0  479.36     .07       0
  574.88     .05       0  851.62      .1       0
#XS Ineff= 2 , 0
          293.97  2396.9
Permanent Ineff=
       F       F
Bank Sta=462.84,479.36
XS Rating Curve= 0 ,0
Exp/Cntr=0.5,0.3

Type RM Length L Ch R = 1 ,975     ,59.7,58.4,57
XS GIS Cut Line= 4
2031648.09748228351983.996166959 2031287.9302236351620.441775963
2031232.60651536351601.2475886342030888.24598362351356.243485466
#Sta/Elev= 30
       0 2403.01   19.68 2400.95  100.13  2398.9  183.25 2397.92  236.19 2397.43
   285.4 2395.58  328.05 2395.57  347.76 2397.23  373.97 2397.71   403.3 2395.13
   498.5 2394.31  528.02 2394.49  531.27 2394.16  534.45 2392.51  537.78 2391.38
  551.43 2393.13  586.69 2394.33  645.82 2394.27  714.46 2397.59   806.2 2399.13
  823.98 2401.57  838.96  2405.3  861.89 2413.56  871.72 2417.99  878.27 2419.21
   901.2 2426.03  917.58 2433.74  947.07 2445.22  966.73 2448.88  992.94 2448.18
#Mann= 10 ,-1 , 0
       0    .055       0  100.13    .035       0  183.25    .055       0
  347.76     .06       0   403.3     .05       0   498.5     .07       0
  534.45    .045       0  551.43     .07       0  645.82     .05       0
  823.98      .1       0
#XS Ineff= 2 , 0
           368.6 2397.85
Permanent Ineff=
       F       F
Bank Sta=534.45,551.43
XS Rating Curve= 0 ,0
Exp/Cntr(USF)=0,0
Exp/Cntr=0.5,0.3

Type RM Length L Ch R = 1 ,916     ,29.3,29.3,29.7
XS GIS Cut Line= 4
2031627.59588285351860.6079622952031316.39801444351561.128902465
2031220.04387642 351544.202099042030880.20006795351290.295126542
#Sta/Elev= 30
       0 2399.54   80.42 2398.64   127.6 2397.36   186.5 2397.42  229.03  2398.8
  242.12 2397.71  253.41  2394.7  316.21 2393.99  375.88 2393.72  461.24 2394.91
  472.12 2393.34  477.55 2391.51  489.42 2393.36  500.37 2394.77  529.72 2393.86
  559.58 2394.31  582.73 2395.22  695.99 2397.62  712.46 2399.28  725.52 2402.65
  758.15 2416.26  777.73 2425.58  787.52 2426.73  797.31 2432.27  810.36 2437.68
  839.73 2447.66  865.83 2450.41   895.2 2450.05  918.05  2447.9  953.94 2442.53
#Mann= 10 ,-1 , 0
       0    .035       0   80.42    .055       0  253.41     .06       0
  316.21     .05       0  375.88     .07       0  472.12    .045       0
  489.42     .07       0  559.58     .06       0  582.73     .05       0
  695.99      .1       0
#XS Ineff= 2 , 0
          457.12 2394.88  504.42         2394.88
Permanent Ineff=
       F       F
Bank Sta=472.12,489.42
XS Rating Curve= 0 ,0
Exp/Cntr=0.5,0.3