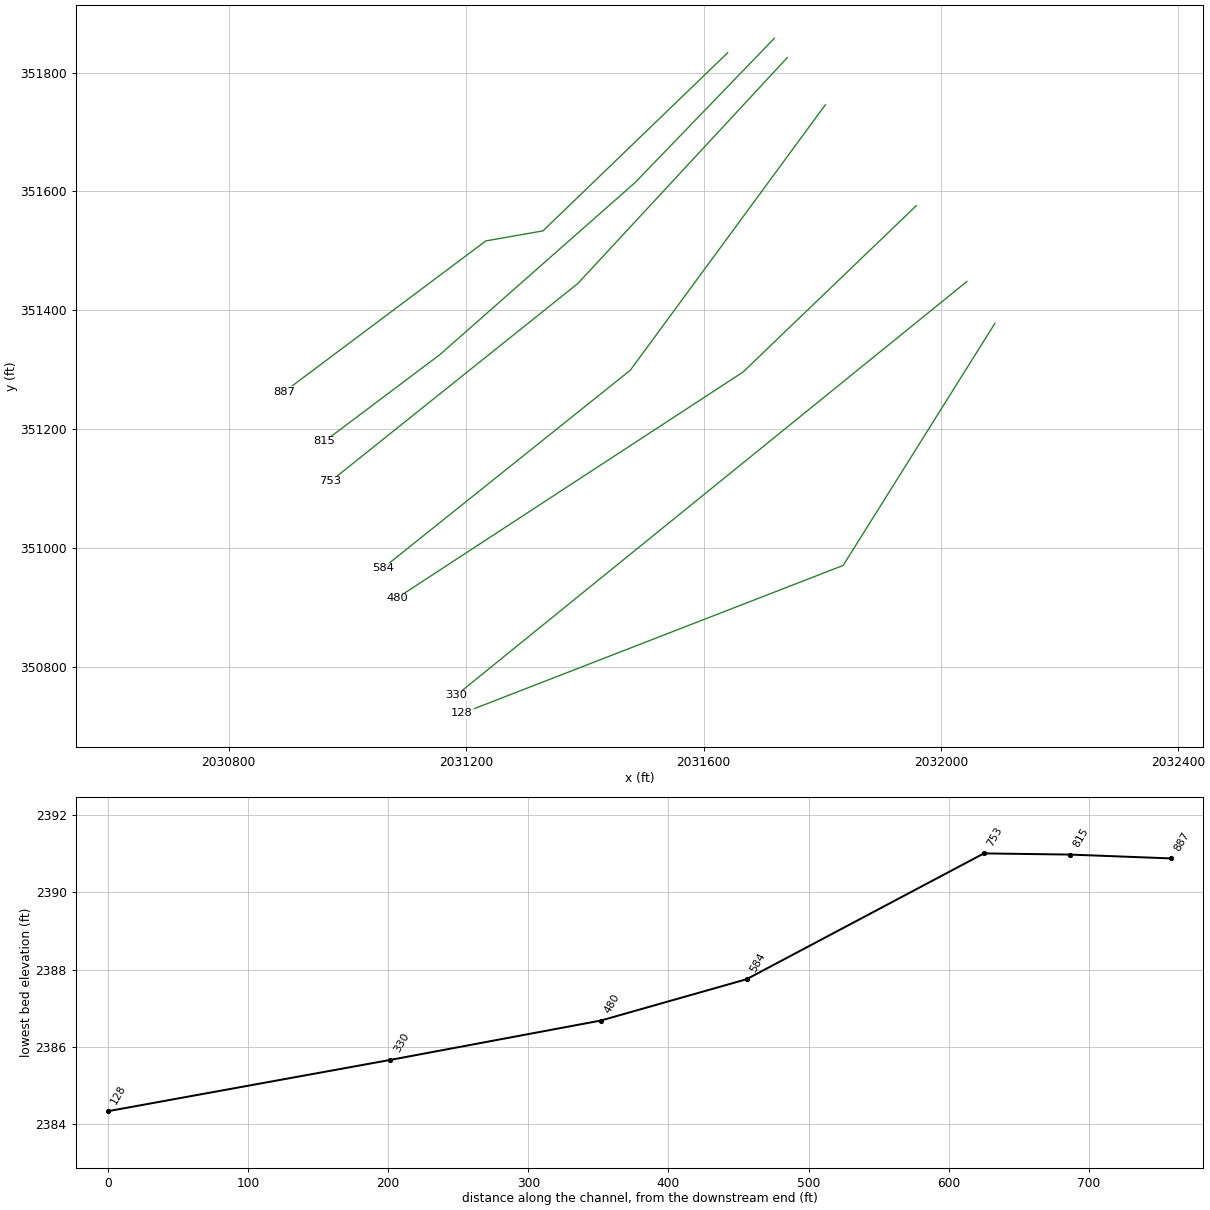
HEC-RAS study WOLFPENCK.prj: WOLFPENCK

--- WOLFPENCK.g01 (geometry) --- (continued)

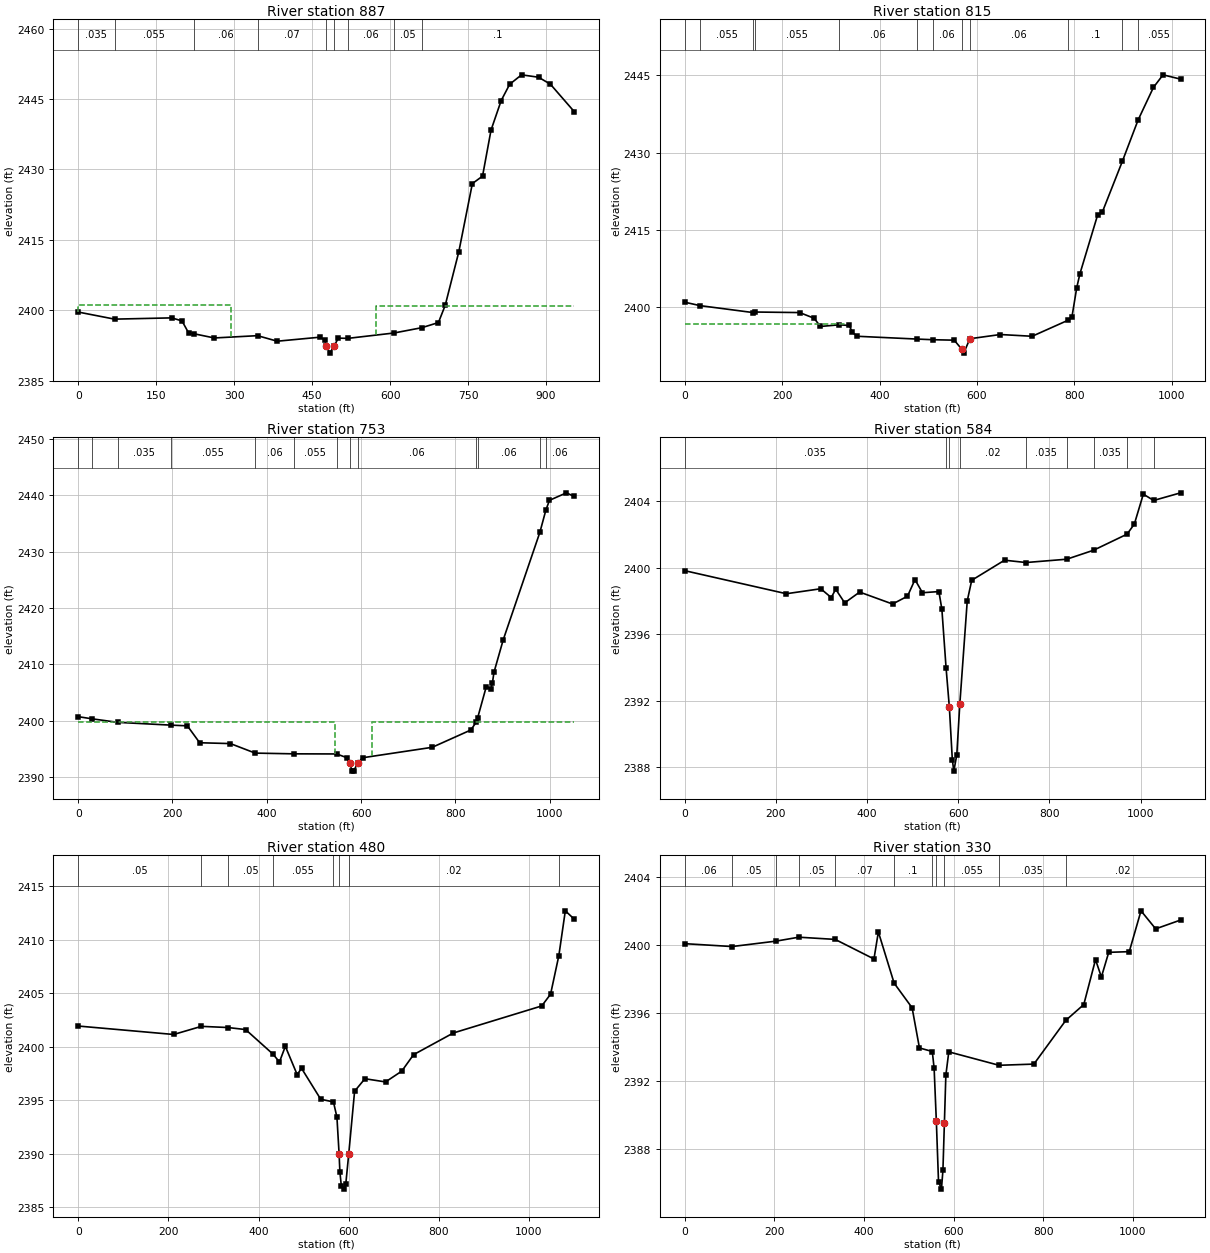
Type RM Length L Ch R = 1 ,887     ,69.1,72.2,77.7
XS GIS Cut Line= 4
2031640.61685418351833.2638568732031329.41898577351533.785125121
2031233.06484778351516.8579936332030893.22103928351262.952005371
#Sta/Elev= 30
       0 2399.63   69.85 2398.12  179.96 2398.39  199.59 2397.74  212.67 2395.12
     222 2395.02  261.75 2394.11  344.92  2394.6  382.81 2393.42   464.5 2394.27
  474.29 2393.73  477.32 2392.47  484.07 2390.88  492.32 2392.44  500.37 2394.08
  518.36 2394.02  607.53 2395.17     661  2396.3  692.88 2397.39  705.94 2401.07
  732.04 2412.45  758.15    2427  777.73 2428.58  794.04 2438.38  813.62 2444.69
  829.94 2448.15  852.78 2450.16  885.41 2449.65  908.26 2448.16  953.94 2442.34
#Mann= 9 ,-1 , 0
       0    .035       0   69.85    .055       0     222     .06       0
  344.92     .07       0  477.32    .045       0  492.32     .07       0
  518.36     .06       0  607.53     .05       0     661      .1       0
#XS Ineff= 2 , 0
          293.97 2401.12  572.03         2400.91
Permanent Ineff=
       F       F
Bank Sta=477.32,492.32
XS Rating Curve= 0 ,0
Exp/Cntr=0.5,0.3

Type RM Length L Ch R = 1 ,815     ,61.9,61.4,61.2
XS GIS Cut Line= 4
2031719.22758935351857.5423516332031484.38521127 351614.79644604
2031155.83107837351325.7592944652030961.63428827351180.111619875
#Sta/Elev= 30
       0 2400.89   31.65 2400.22  140.52 2398.87  143.65 2398.98   236.1 2398.87
  265.61 2397.77  278.73 2396.17  317.55 2396.49  337.75 2396.36  344.28 2395.03
  354.08 2394.26  475.94 2393.72  509.34 2393.59  553.28  2393.5  568.86 2391.74
  572.88 2390.98  585.42 2393.78  647.99  2394.6   713.3 2394.26  787.52  2397.4
  795.03 2398.04  804.87 2403.73  811.43 2406.44  847.52  2417.8  857.36 2418.42
  898.44 2428.29  930.74 2436.33  962.33 2442.69  982.01 2445.13 1018.09 2444.29
#Mann= 12 ,-1 , 0
       0    .035       0   31.65    .055       0  140.52    .035       0
  143.65    .055       0  317.55     .06       0  475.94     .07       0
  509.34     .06       0  568.86    .045       0  585.42     .06       0
  787.52      .1       0  898.44     .06       0  930.74    .055       0
#XS Ineff= 2 , 0
          327.39 2396.74
Permanent Ineff=
       F       F
Bank Sta=568.86,585.42
XS Rating Curve= 0 ,0
Exp/Cntr(USF)=0,0
Exp/Cntr=0.5,0.3

Type RM Length L Ch R = 1 ,753     ,169.4,169.3,169.2
XS GIS Cut Line= 3
2031741.11206003351825.1408416332031388.12490509351445.259055465
2030971.26386218351112.443120047
#Sta/Elev= 30
       0 2400.68   30.06 2400.29   83.89 2399.67  196.27 2399.18  231.56 2399.05
  257.65 2396.05  322.88  2395.9  375.39 2394.21  457.61 2394.08  548.25 2394.06
  570.93 2393.36  575.75 2392.43  580.74 2391.08  584.02 2391.01  592.93 2392.42
  603.65 2393.39  750.92 2395.24  832.73 2398.31  844.12 2399.68  846.99 2400.38
  865.45 2405.97  875.27 2405.64  878.54 2406.61  881.82 2408.53  901.45 2414.31
  979.32 2433.43  992.05 2437.38  999.63  2439.1 1035.63 2440.43 1051.99 2439.79
#Mann= 13 ,-1 , 0
       0    .035       0   30.06    .055       0   83.89    .035       0
  196.27    .055       0  375.39     .06       0  457.61    .055       0
  548.25     .06       0  575.75    .045       0  592.93     .06       0
  844.12      .1       0  846.99     .06       0  979.32    .055       0
  992.05     .06       0
#XS Ineff= 2 , 0
          545.75  2399.8  622.93          2399.8
Permanent Ineff=
       F       F
Bank Sta=575.75,592.93
XS Rating Curve= 0 ,0
Exp/Cntr=0.5,0.3

Type RM Length L Ch R = 1 ,584     ,104.6,103.9,102.5
XS GIS Cut Line= 3
 2031805.1988741351745.7600948812031476.55386211 351299.40993771
2031059.69314726 350966.59301804
#Sta/Elev= 30
       0 2399.83  223.03 2398.44  298.46 2398.74  321.42 2398.21  331.26 2398.71
  350.94 2397.89  383.74 2398.54  455.89 2397.82  488.69 2398.29  505.09 2399.29
  521.49  2398.5  557.56 2398.57  564.11  2397.5  573.33 2393.96  580.51  2391.6
  587.01 2388.44  590.29 2387.75  596.83 2388.74  603.41 2391.78  619.74 2398.01
  629.56 2399.25  701.55 2400.46  748.76 2400.32  837.98 2400.52   896.7 2401.06
  970.31 2402.03  986.26 2402.64  1005.9 2404.44 1028.62 2404.06 1087.71 2404.52
#Mann= 9 ,-1 , 0
       0    .035       0  573.33     .02       0  580.51    .045       0
  603.41     .02       0  748.76    .035       0  837.98     .02       0
   896.7    .035       0  970.31     .02       0 1028.62    .035       0
Bank Sta=580.51,603.41
XS Rating Curve= 0 ,0
Exp/Cntr=0.5,0.3

Type RM Length L Ch R = 1 ,480     ,146.4,150.2,149
XS GIS Cut Line= 3
2031958.29108761351576.0048569592031666.62402003351296.490980297
 2031083.2908691350916.283079296
#Sta/Elev= 30
       0 2401.94  211.76 2401.15  273.27 2401.91  332.19  2401.8   371.4 2401.61
  431.93 2399.32  446.47 2398.58  459.55 2400.04   485.7  2397.4  495.51 2397.98
  538.01 2395.09  566.25 2394.84  573.97 2393.42  578.76 2390.01   580.5 2388.32
  583.77 2386.96  590.31 2386.68  593.58 2387.14  600.09 2389.93  613.19 2395.84
  636.08 2397.01  681.84 2396.71   717.8 2397.72  743.96 2399.26  832.22 2401.29
 1028.36 2403.82 1047.97 2404.92 1066.37 2408.54 1080.66 2412.72 1100.28 2411.95
#Mann= 8 ,-1 , 0
       0     .05       0  273.27     .06       0  332.19     .05       0
  431.93    .055       0  566.25     .02       0  578.76    .045       0
  600.09     .02       0 1066.37    .035       0
Bank Sta=578.76,600.09
XS Rating Curve= 0 ,0
Exp/Cntr=0.3,0.1

Type RM Length L Ch R = 1 ,330     ,204.1,201.6,197.6
XS GIS Cut Line= 2
2032043.67215045351448.6209253822031183.05608954350752.731897205
#Sta/Elev= 30
       0 2400.09   105.7 2399.92  204.24 2400.24  254.66 2400.47  335.81 2400.34
   422.4 2399.19  432.23 2400.78  467.39 2397.77  507.54 2396.32  523.91 2393.96
  552.58 2393.75  556.66 2392.77   561.6 2389.67  566.48  2386.1  573.03 2385.66
   576.3 2386.76  579.58 2389.54  582.85 2392.36   589.4 2393.73  701.53 2392.94
  779.32 2393.01  850.49 2395.58  890.65 2396.51  916.84 2399.15  929.94 2398.13
  946.31 2399.58  992.16 2399.62 1018.35 2402.02  1051.1 2400.96 1106.76 2401.48
#Mann= 11 ,-1 , 0
       0     .06       0   105.7     .05       0  204.24     .06       0
  254.66     .05       0  335.81     .07       0  467.39      .1       0
  552.58    .055       0   561.6    .045       0  579.58    .055       0
  701.53    .035       0  850.49     .02       0
Bank Sta=561.6,579.58
XS Rating Curve= 0 ,0
Exp/Cntr=0.3,0.1

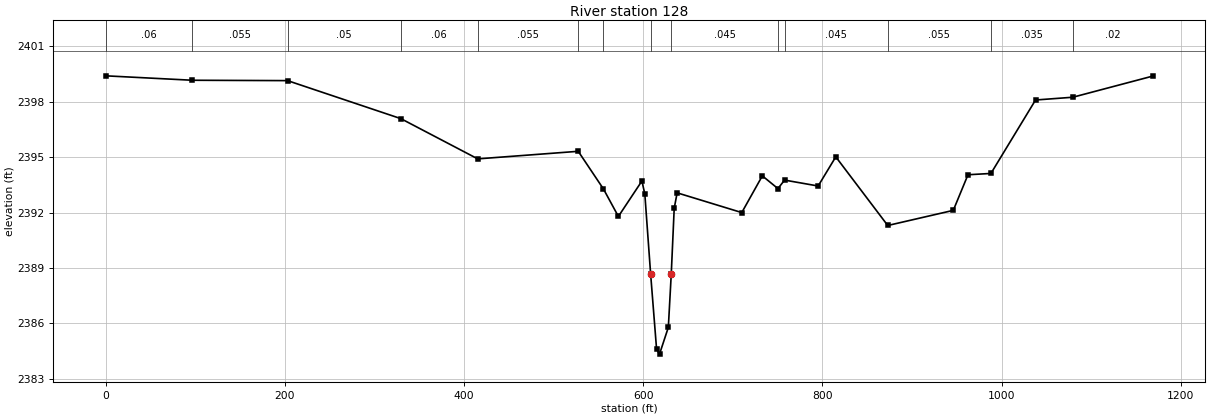
Type RM Length L Ch R = 1 ,128     ,128.43,128.43,128.43
XS GIS Cut Line= 3
2032090.73701693351378.0239537062031835.24212112 350971.24786438
2031193.14104311 350722.47605221
#Sta/Elev= 30
       0 2399.41   96.73 2399.17  202.87 2399.15  329.38 2397.09  415.16 2394.91
  527.36 2395.32  555.49 2393.28  572.17 2391.79  598.41 2393.71  601.68 2393.01
  608.18 2388.66   614.8  2384.6  618.08 2384.33  627.92 2385.78  631.18 2388.66
  634.48 2392.23  637.75 2393.07   709.9    2392  732.85 2393.99  750.25  2393.3
  757.68 2393.76  795.15 2393.44  814.83 2395.02  872.84  2391.3  945.99 2392.12
  962.39 2394.05     988 2394.12 1037.81  2398.1 1079.42 2398.25 1168.97  2399.4
#Mann= 14 ,-1 , 0
       0     .06       0   96.73    .055       0  202.87     .05       0
  329.38     .06       0  415.16    .055       0  527.36     .06       0
  555.49    .045       0  608.18    .045       0  631.18    .045       0
  750.25      .1       0  757.68    .045       0  872.84    .055       0
     988    .035       0 1079.42     .02       0
Bank Sta=608.18,631.18
XS Rating Curve= 0 ,0
Exp/Cntr=0.3,0.1
LCMann Table=0

Chan Stop Cuts=-1
Use User Specified Reach Order=0
Composite Channel Slope=5